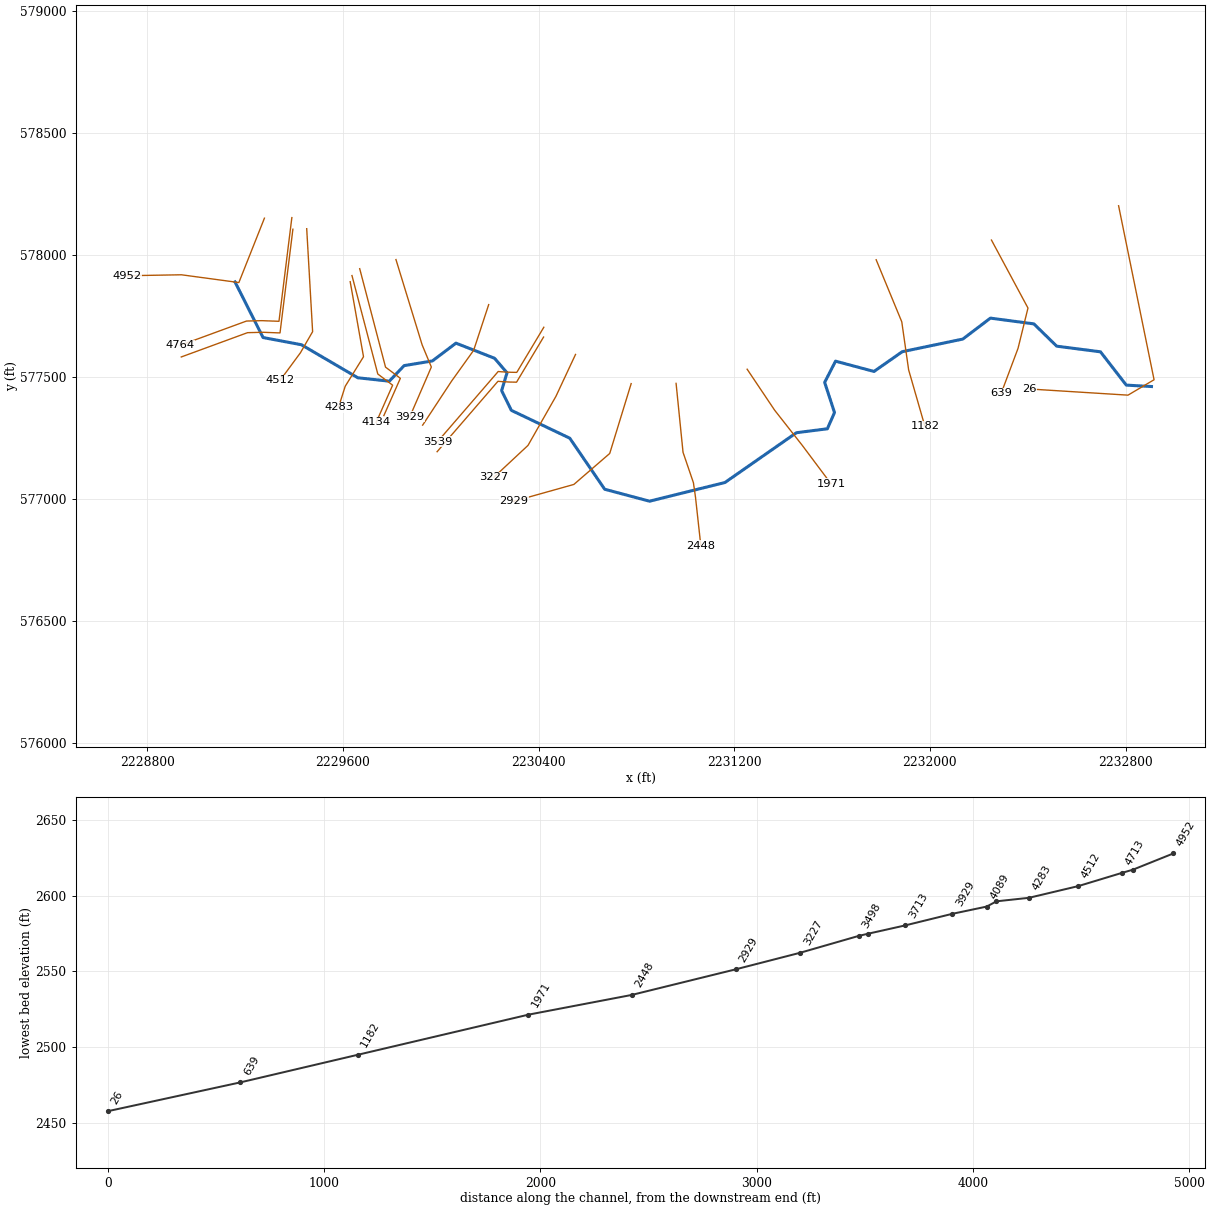
--- STONYRN.prj (project) ---

Proj Title=STONYRN
Current Plan=p01
Default Exp/Contr=0,0
English Units
Geom File=g01
Flow File=f01
Plan File=p01
BEGIN DESCRIPTION:
----------MODEL BY WOOD PLC 2022----------
AFH study
Randolph County, WV
HEC-RAS Version: RAS 6.2
Vertical Datum: NAVD88
Projection: NAD 1983 StatePlane West Virginia S FIPS 4702 (US Feet)
Terrain: 1-meter LIDAR (FEMA Region III 3DEP collected 2016-2018)
Land Use: 2019 NLCD
Hydrologic Method:
WV SIR2010-5033 regression equations
Additional Model Notes:
None
END DESCRIPTION:
DSS Export Rating Curves= 0
DSS Export Rating Curve Sorted= 0
DSS Export Volume Flow Curves= 0
DXF OffsetX= 0
DXF OffsetY= 0
DXF ScaleX= 0
DXF ScaleY= 0

--- STONYRN.p01 (plan) ---

Plan Title=Floodplain
Program Version=6.20
Short Identifier=Floodplain
Geom File=g01
Flow File=f01
Subcritical Flow
K Sum by GR= 0
Std Step Tol= 0.01
Critical Tol= 0.01
Num of Std Step Trials= 20
Max Error Tol= 0.3
Flow Tol Ratio= 0.001
Split Flow NTrial= 30
Split Flow Tol= 0.02
Split Flow Ratio= 0.02
Log Output Level= 0
Friction Slope Method= 1
Unsteady Friction Slope Method= 2
Unsteady Bridges Friction Slope Method= 1
Parabolic Critical Depth
Global Vel Dist= 0 , 0 , 0
Global Log Level= 0
CheckData=True
Encroach Param=-1 ,0,0, 0
Mapping Interval=1HOUR
Computation Time Step Use Courant=        0
Computation Time Step Use Time Series=    0
Computation Time Step Count To Double=0
Computation Time Step Max Doubling=0
Computation Time Step Max Halving=0
Computation Time Step Residence Courant=0
Run HTab= 0
Run UNet= 0
Run Sediment= 0
Run PostProcess= 0
Run WQNet= 0
Run RASMapper=-1
UNET Theta= 0
UNET Theta Warmup= 0
UNET ZTol= 0
UNET ZSATol= 0
UNET MxIter= 0
UNET Max Iter WO Improvement= 0
UNET MaxInSteps= 0
UNET DtIC= 0
UNET DtMin= 0
UNET MaxCRTS= 0
UNET WFStab= 0
UNET SFStab= 0
UNET WFX= 1
UNET SFX= 1
UNET Gravity=32.174
UNET 1D Methodology=Finite Difference
UNET DSS MLevel= 1
UNET Pardiso=0
UNET DZMax Abort= 0
UNET Use Existing IB Tables= 0
UNET Froude Reduction=False
UNET Froude Limit= 0
UNET Froude Power= 0
UNET D1 Cores= 0
UNET WindReference=Eulerian
UNET WindDragFormulation=Hsu (1988)
UNET D2 Coriolis=0
UNET D2 Cores= 0
UNET D2 Theta= 1
UNET D2 Theta Warmup= 1
UNET D2 Z Tol= 0.01
UNET D2 Volume Tol= 0.01
UNET D2 Max Iterations= 20
UNET D2 Equation= 0
UNET D2 RampUpFraction=0.1
UNET D2 TimeSlices= 1
UNET D2 Turbulence Formulation=Non-Conservative (original)
UNET D2 Eddy Viscosity=0.3
UNET D2 Transverse Eddy Viscosity=0.1
UNET D2 Smagorinsky Mixing=0
UNET D2 BCVolumeCheck=0
UNET D2 Cores=0
UNET D2 SolverType=PARDISO (Direct)
UNET D2 Minimum Iterations= 2147483647
UNET D2 Maximum Iterations= 2147483647
UNET D2 Restart Number= 10
UNET D2 Relaxation Coeff=1.3
UNET D2 SOR Precondition Iterations= 10
UNET D2 ILUT Maximum Fill= 8
UNET D2 ILUT Tolerance=1E-08
UNET D1D2 MaxIter= 0
UNET D1D2 ZTol=0.01
UNET D1D2 QTol=0.1
UNET D1D2 MinQTol=1
Write IC File= 0
Write IC File at Fixed DateTime=0
Write IC File at Sim End=0
Echo Input=False
Echo Parameters=False
Echo Output=False
Write Detailed= 0
HDF Write Warmup=0
HDF Write Time Slices=0
HDF Flush=0
HDF Compression= 1
HDF Chunk Size= 1
HDF Spatial Parts= 1
HDF Use Max Rows=0
HDF Fixed Rows= 1
Calibration Method= 0
Calibration Iterations= 20
Calibration Max Change=0.05
Calibration Tolerance=0.2
Calibration Maximum=1.5
Calibration Minimum=0.5
Calibration Optimization Method= 1
WQ AD Non Conservative
WQ ULTIMATE=-1
WQ Max Comp Step=1HOUR
WQ Output Interval=15MIN
WQ Output Selected Increments= 0
WQ Output face flow=0
WQ Output face velocity=0
WQ Output face area=0
WQ Output face dispersion=0
WQ Output cell volume=0
WQ Output cell surface area=0
WQ Output cell continuity=0
WQ Output cumulative cell continuity=0
WQ Output face conc=0
WQ Output face dconc_dx=0
WQ Output face courant=0
WQ Output face peclet=0
WQ Output face adv mass=0
WQ Output face disp mass=0
WQ Output cell mass=0
WQ Output cell source sink temp=0
WQ Output nsm pathways=0
WQ Output nsm derived pathways=0
WQ Create Restart=0
WQ Fixed Restart=0
WQ System Summary=0
WQ Write To DSS=0
Sorting and Armoring Iterations= 10
XS Update Threshold= 0.02
Bed Roughness Predictor= 0
Hydraulics Update Threshold= 0.02
Energy Slope Method= 1
Volume Change Method= 1
Sediment Retention Method= 0
Sediment TS Multiplier= 1
Warm Up Method= 0
XS Weighting Method= 0
Number of US Weighted Cross Sections= 1
Number of DS Weighted Cross Sections= 1
Upstream XS Weight=0
Main XS Weight=1
Downstream XS Weight=0
Number of DS XS's Weighted with US Boundary= 1
Upstream Boundary Weight= 1
Weight of XSs Associated with US Boundary= 0
Number of US XS's Weighted with DS Boundary= 1
Downstream Boundary Weight= 0.5
Weight of XSs Associated with DS Boundary= 0.5
Percentile Method= 0
Sediment Output Level= 3
Mass or Volume Output= 0
Output Increment Type= 1
Profile and TS Output Increment= 1
Transport Output Increment 1
XS Output Flag= 0
XS Output Increment= 10
Read HDF5 Sediment Hotstart= 0
Sediment Hotstart Type= 0
Write Gradation File= 0
Read Gradation Hotstart= 0
Write HDF5 File= 1
Write Binary Output= 1
Write DSS Sediment File= 0
DSS Sediment Output Type= 1
SV Curve= 0
Specific Gage Flag= 0
Subcell Erosion Methods= 0
Subcell Deposition Methods= 0
Advection Scheme= 1
Matrix Solver= 0
Implicit Weighting Factor= 1
Maximum Outer Loop Convergence Iterations= 5
Convergence Maximum Absolute= 0.001
Convergence RMSE= 0.0001
Grain Fractions Max Abs Error= 0.001
Max Subgrid Regions= 1
Max Subgrid Length Scale= 3.402823E+38
Initial Layer Thickness= 3.402823E+38
Min Layer Thickness= 3.402823E+38
Max Layer Thickness= 3.402823E+38
Number of Layers= 5

--- STONYRN.f01 (steady flow) ---

Flow Title=Flow
Program Version=6.20
Number of Profiles= 1
Profile Names=P100yr
River Rch & RM=STONYRN,Main,4952
     437
River Rch & RM=STONYRN,Main,1182
     511
Boundary for River Rch & Prof#=STONYRN,Main            , 1
Up Type= 0
Dn Type= 3
Dn Slope=0.03345
DSS Import GetInterval= 0
DSS Import GetPeak= 0
DSS Import FillOption= 0

--- STONYRN.g01 (geometry) ---

Geom Title=Geometry
Program Version=6.20

River Reach=STONYRN         ,Main
Reach XY= 30
2229158.96800004 577890.760000022229273.72500001577662.894999996
2229430.40899999577633.3819999992229661.31200004577497.965000004
2229789.78399999 577484.076000022229850.54800001577547.878000021
2229966.00000001577566.9749999942230062.35400003577639.892000005
      2230220.34577577.8260000052230271.12100001577518.364000008
     2230248.986577445.447999999      2230288.83577364.545000017
2230527.63200003577250.4819999932230670.34000002577041.368000016
2230853.60400002576992.3570000082231162.19800003      577068.963
2231454.29799999      577272.9562231580.83600001577289.033000007
2231610.00200002577355.7000000032231569.74600002577479.093999997
2231614.23400003577566.1169999992231771.48199998 577523.92900002
2231887.04200001      577604.875      2232134.72577656.675999999
2232247.39400001577742.4089999942232425.08499999577718.841000006
2232518.50899999577627.4780000152232697.40500003577604.387999997
2232802.87300001 577467.929000022232905.94894924577462.144279014

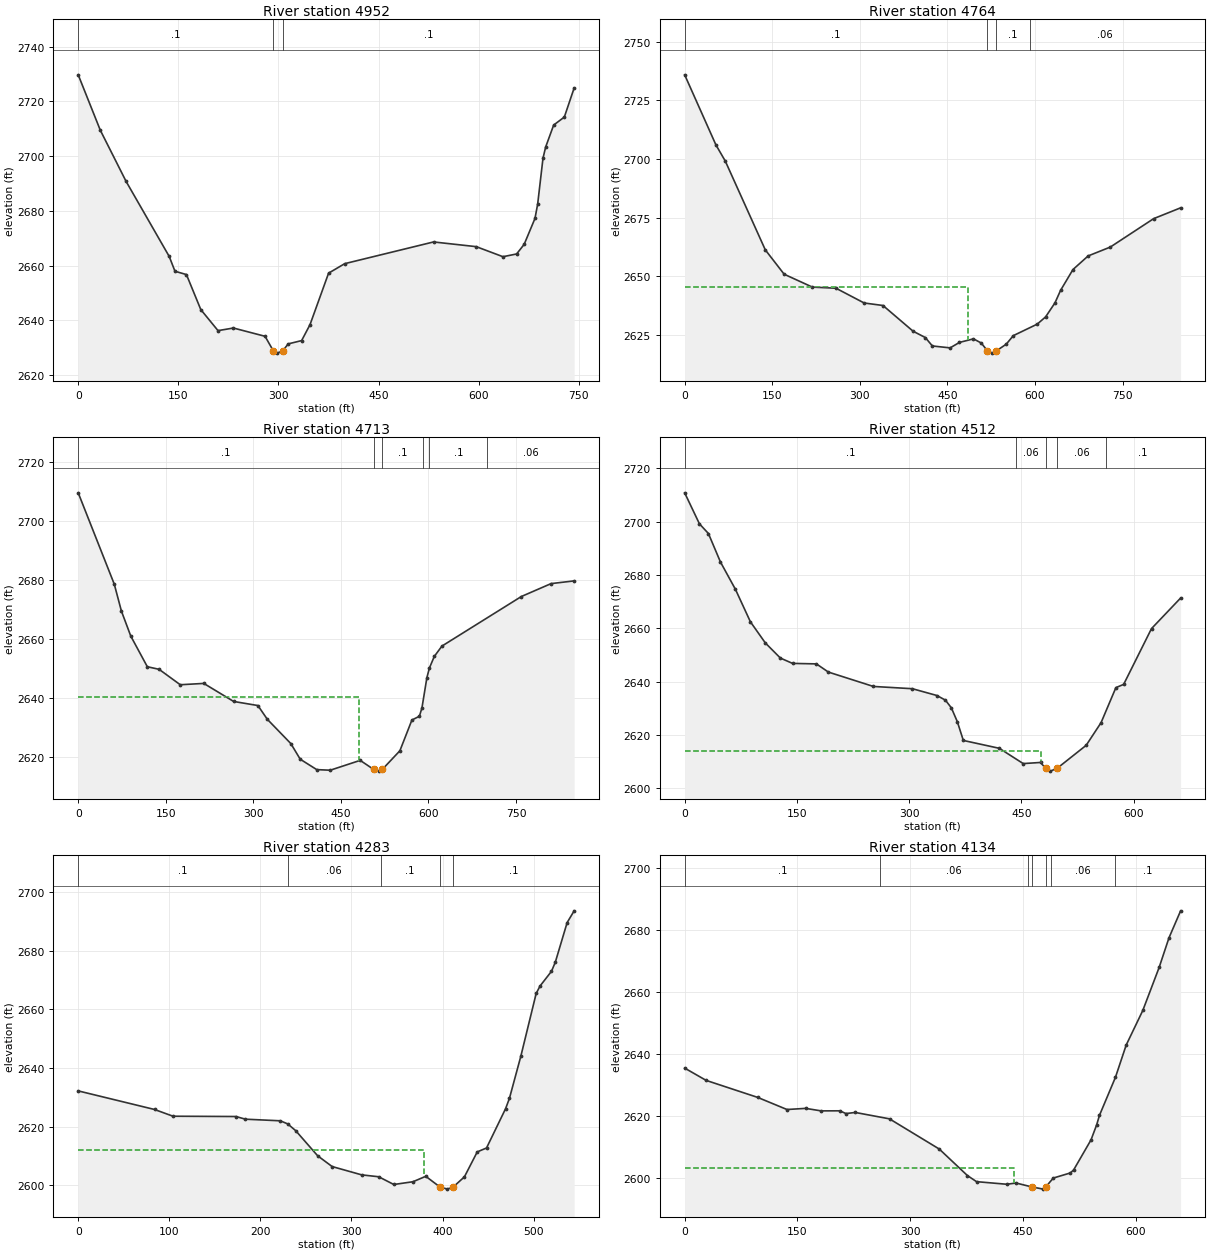
Type RM Length L Ch R = 1 ,4952    ,186,187.6,188.6
XS GIS Cut Line= 4
2229279.30517082578151.9746646542229174.78668639577888.176978364
2228939.91519172577920.0023944522228717.50147938577916.112958767
#Sta/Elev= 30
       0 2729.69    33.1 2709.45    71.8 2690.73   136.4 2663.32     145 2657.92
   162.2 2656.71   183.7 2643.92   209.5 2636.23   232.6 2637.18     280 2634.16
  292.152628.946   298.5 2628.01  306.962628.948   314.6 2631.38   334.8 2632.59
   347.4 2638.43   375.2 2657.23   399.4  2660.7   532.5 2668.63   596.5 2666.91
   636.5 2663.24     657 2664.24   668.3 2667.76   684.5 2677.23   688.5 2682.42
   696.5  2699.2   700.5 2703.31   712.5 2711.34   728.5 2714.26   743.2 2724.89
#Mann= 3, -1 ,  0
       0     0.1       0  292.15   0.045       0  306.96     0.1       0
Bank Sta=292.15,306.96
XS Rating Curve= 0 ,0
Exp/Cntr=0.3,0.1

Type RM Length L Ch R = 1 ,4764    ,50.2,50.6,50.3
XS GIS Cut Line= 5
2229391.41350181578154.2669854372229338.76714685577729.423144181
2229268.67208775577732.0420745492229205.95485483577730.460967837
2228935.11582941577630.949566866
#Sta/Elev= 30
       0 2735.86    53.5    2706    69.6 2699.08   138.1 2661.25   170.4 2650.87
   218.7 2645.38   259.1 2644.91   307.4 2638.61   339.7 2637.54   391.2 2626.59
   412.2 2623.88   424.3 2620.29   454.7 2619.48   470.7 2621.81   494.7 2623.32
   508.1 2621.54  518.682618.188   526.7 2617.24  533.862618.187   550.8 2621.05
   562.9 2624.69   603.9  2629.6   618.3  2632.7   634.3 2638.67   643.8 2643.96
   665.1 2652.87   691.1 2658.67   729.1 2662.45   803.3 2674.56   849.5 2679.17
#Mann= 4, -1 ,  0
       0     0.1       0  518.68   0.045       0  533.86     0.1       0
  590.97    0.06       0
#XS Ineff= 2 , 0
          485.92 2645.38
Permanent Ineff=
       F       F
Bank Sta=518.68,533.86
XS Rating Curve= 0 ,0
Exp/Cntr(USF)=0,0
Exp/Cntr=0.3,0.1

Type RM Length L Ch R = 1 ,4713    ,194.6,200.9,208.5
XS GIS Cut Line= 5
2229395.64264605578106.6383592852229342.99629108577681.794518029
2229272.90123198577684.4134483972229210.18399907577682.832341685
2228939.34497365577583.320940714
#Sta/Elev= 30
       0  2709.6    61.8 2678.58      74 2669.46    90.1 2660.95   118.4 2650.57
   138.5  2649.7   174.8 2644.46   215.1 2644.91   266.2 2638.79   307.8  2637.4
   323.9 2632.74   364.2 2624.49   380.3 2619.18   408.6 2615.65   431.7 2615.45
     483 2618.79     506 2615.73     515 2615.14  520.942615.733     551 2622.05
   571.6 2632.49   584.4 2633.76   588.8  2636.6   597.2 2646.81   601.5 2650.11
     610 2654.09     623 2657.58   759.1 2674.41     810 2678.79   849.5 2679.71
#Mann= 6, -1 ,  0
       0     0.1       0     506   0.045       0  520.94     0.1       0
  590.97    0.06       0  600.97     0.1       0  700.97    0.06       0
#XS Ineff= 2 , 0
          480.87 2640.14
Permanent Ineff=
       F       F
Bank Sta=506,520.94
XS Rating Curve= 0 ,0
Exp/Cntr(USF)=0,0
Exp/Cntr=0.3,0.1

Type RM Length L Ch R = 1 ,4512    ,229.2,229,228.8
XS GIS Cut Line= 4
2229452.13053786578108.8516812582229476.31654326577686.898478746
2229426.31230014 577600.189099882229343.38856185577487.530182427
#Sta/Elev= 30
       0 2710.85    19.7 2699.22    31.7 2695.59    47.8  2684.9    67.8 2674.65
    87.8 2662.47   107.8 2654.52   127.9 2648.85   144.1 2646.86     176 2646.67
     192  2643.6   252.1 2638.21   304.2 2637.36     337 2634.81   348.4 2633.06
   356.3 2630.18   364.3 2624.96   372.3 2617.95   420.4    2615   452.3 2609.27
   475.4 2609.69   482.52607.433   488.4 2606.44  497.34 2607.43   536.4 2616.12
   556.3 2624.62   576.1 2637.76   586.5 2638.99   623.7 2659.91   662.6 2671.38
#Mann= 5, -1 ,  0
       0     0.1       0  442.65    0.06       0   482.5   0.045       0
  497.34    0.06       0  562.74     0.1       0
#XS Ineff= 2 , 0
          475.47 2614.16
Permanent Ineff=
       F       F
Bank Sta=482.5,497.34
XS Rating Curve= 0 ,0
Exp/Cntr=0.3,0.1

Type RM Length L Ch R = 1 ,4283    ,141.9,149.9,165.2
XS GIS Cut Line= 4
 2229629.9387523577891.6816854422229684.35358947577584.237855393
2229609.53318836577463.1648426742229582.32576977577377.461474121
#Sta/Elev= 30
       0 2632.18    83.8 2625.84   104.1 2623.54   173.2 2623.44   183.6 2622.53
   221.9 2621.98     230 2620.92   238.8 2618.61   262.9 2610.04   278.8 2606.37
   311.3 2603.53   329.9 2602.89   346.5 2600.25   367.5 2601.19   381.6 2603.04
   396.72599.501   405.2 2598.67     412 2599.48     424 2602.85   438.1 2611.37
   448.3 2612.71   469.2  2626.1   473.4 2629.59   485.9 2643.93   502.8 2665.41
     507 2667.94   519.6 2672.97   523.8 2676.07   536.8  2689.6   544.5 2693.61
#Mann= 5, -1 ,  0
       0     0.1       0     230    0.06       0  332.22     0.1       0
   396.7   0.045       0     412     0.1       0
#XS Ineff= 2 , 0
          379.93 2612.02
Permanent Ineff=
       F       F
Bank Sta=396.7,412
XS Rating Curve= 0 ,0
Exp/Cntr(USF)=0,0
Exp/Cntr=0.3,0.1

Type RM Length L Ch R = 1 ,4134    ,44.2,44.9,43.1
XS GIS Cut Line= 4
2229637.23566634577916.8023097582229742.80626707577513.485260601
2229803.42589841577467.6647880842229736.02986733 577315.01916581
#Sta/Elev= 30
       0  2635.4    28.6 2631.43    97.1 2625.95   136.1 2622.04   160.9 2622.41
   181.5  2621.6   206.3 2621.62   214.6 2620.74     227 2621.09   272.5 2619.03
   338.7 2609.29   376.2 2600.73   388.3 2598.77   428.6 2597.93   440.9 2598.33
  461.51 2597.09   477.1 2596.36  480.472597.089   490.4 2599.93   513.1 2601.58
   517.5 2602.56   540.6 2612.25   548.1 2617.09   551.8 2620.14   573.1 2632.43
   587.4 2642.84   609.5    2654   631.2 2667.85   644.3 2677.41   659.8 2686.13
#Mann= 7, -1 ,  0
       0     0.1       0     260    0.06       0  456.91     0.1       0
  461.51   0.045       0  480.47     0.1       0  486.91    0.06       0
  572.89     0.1       0
#XS Ineff= 2 , 0
          438.01 2603.08
Permanent Ineff=
       F       F
Bank Sta=461.51,480.47
XS Rating Curve= 0 ,0
Exp/Cntr(USF)=0,0
Exp/Cntr=0.3,0.1

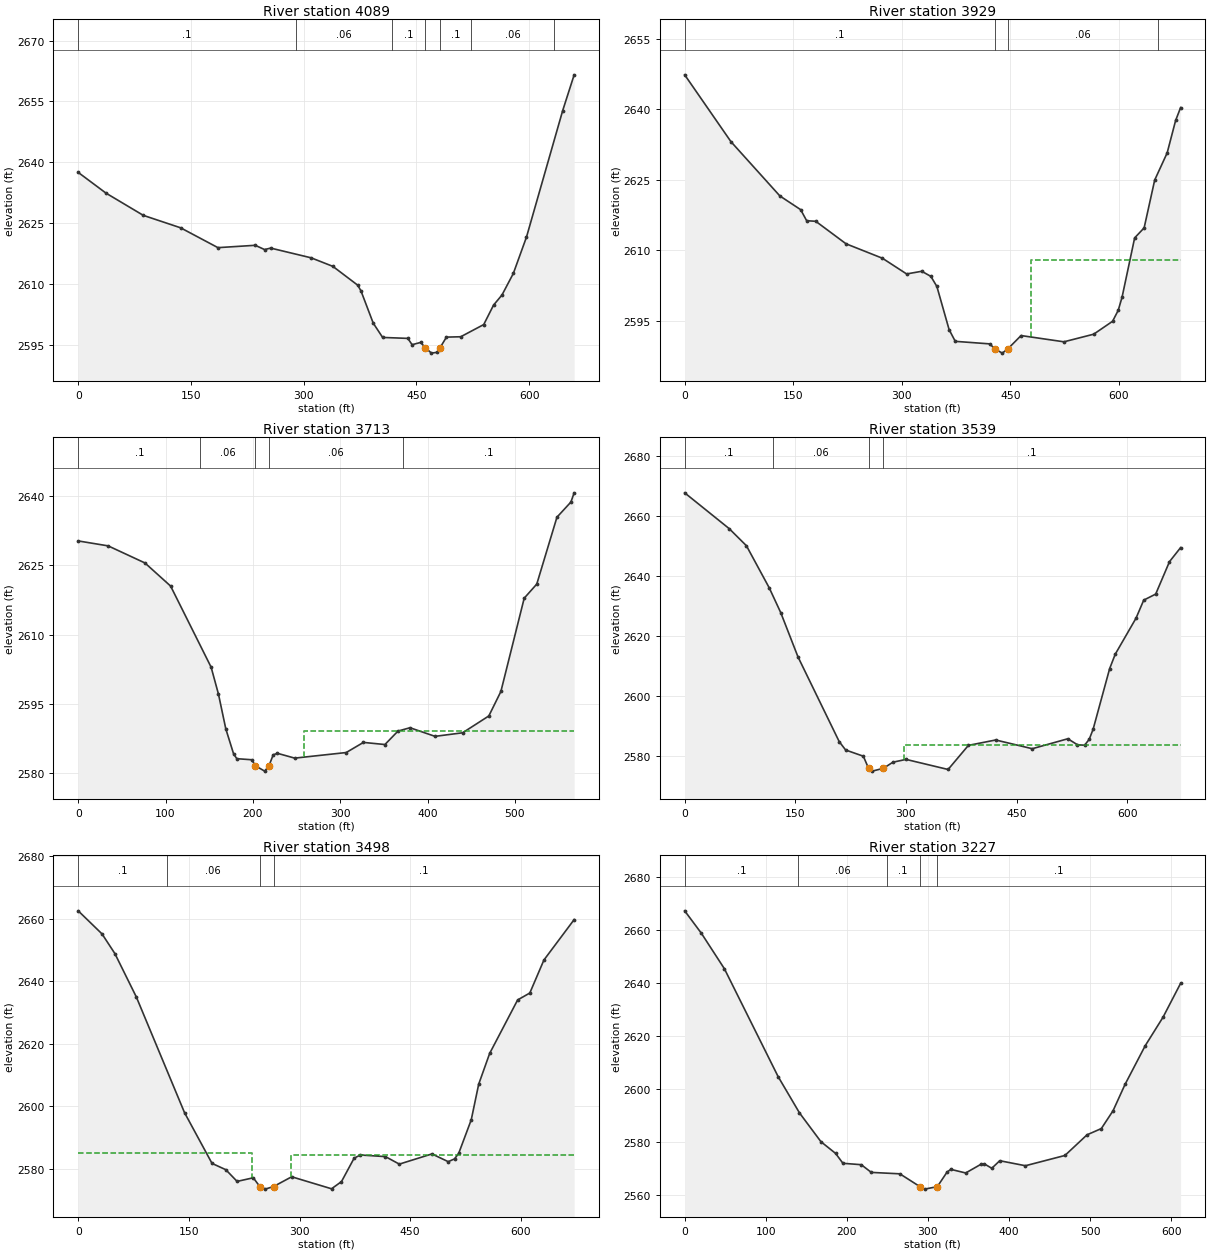
Type RM Length L Ch R = 1 ,4089    ,163.1,159.2,152.9
XS GIS Cut Line= 4
2229668.82617845577944.9776313672229774.39677917 577541.66058221
2229835.01641052577495.8401096942229767.62037944 577343.19448742
#Sta/Elev= 30
       0 2637.49      37 2632.37    86.6 2626.89   136.2 2623.82   185.9 2618.92
   235.5  2619.5   247.9 2618.45   256.1 2618.81   309.9 2616.41   338.8  2614.3
   371.9 2609.65   376.2 2608.24   392.5 2600.29     405 2596.76   438.5 2596.53
   444.2 2594.97   455.6 2595.53  461.622594.271   469.9 2592.89   477.4 2593.09
  481.532594.271   489.9 2596.84   508.9 2596.93   539.5 2599.94   552.6 2604.75
   563.8 2607.24   578.9 2612.56   596.4 2621.54   644.5 2652.71   659.8 2661.57
#Mann= 7, -1 ,  0
       0     0.1       0     290    0.06       0  416.91     0.1       0
  461.62   0.045       0  481.53     0.1       0  522.89    0.06       0
  632.89     0.1       0
Bank Sta=461.62,481.53
XS Rating Curve= 0 ,0
Exp/Cntr(USF)=0,0
Exp/Cntr=0.3,0.1

Type RM Length L Ch R = 1 ,3929    ,225.4,216.4,210.5
XS GIS Cut Line= 4
2229817.03395439577982.3182667632229924.16568657577632.614142451
2229961.72196575577542.0981807832229874.00702012577338.890300338
#Sta/Elev= 30
       0 2647.36    63.9 2633.13   131.5 2621.57   160.2 2618.65   168.5  2616.3
   181.1 2616.17   222.9 2611.38   273.1 2608.31   306.6 2604.96   327.5 2605.53
   340.1 2604.44   348.4 2602.29   365.3  2593.1   373.8 2590.61   421.4 2590.07
  428.422589.015   438.7  2588.1  446.472589.014   464.7 2591.84   523.9 2590.51
     565 2592.13   591.1 2594.88   598.9 2597.21   604.2    2600   621.6 2612.64
   634.7 2614.77   649.3 2624.96   666.5 2630.73   678.2 2637.64   685.1 2640.39
#Mann= 4, -1 ,  0
       0     0.1       0  428.42   0.045       0  446.47    0.06       0
  653.74     0.1       0
#XS Ineff= 2 , 0
                          478.63            2608
Permanent Ineff=
       F       F
Bank Sta=428.42,446.47
XS Rating Curve= 0 ,0
Exp/Cntr=0.3,0.1

Type RM Length L Ch R = 1 ,3713    ,180,174.1,161.1
XS GIS Cut Line= 4
2230196.16439996577797.7448834862230134.71610918577610.565401213
2230044.64124895577484.6123129362229926.16577505577303.952120562
#Sta/Elev= 30
       0 2630.26    34.3 2629.19    76.4  2625.5   105.8  2620.5   152.2 2602.96
   160.6 2597.14     169 2589.63   177.9 2584.24   181.6 2583.18   198.7 2582.95
     2032581.635   213.5 2580.49   218.4 2581.63   223.3 2584.02   228.2 2584.34
   247.9  2583.3   306.9 2584.51   326.6  2586.7   351.2 2586.24   366.2 2589.15
   379.9 2589.87   408.6 2588.01   440.2 2588.78   470.2 2592.42     484 2597.71
   510.7 2617.88   525.1 2620.93   548.2 2635.39   564.2 2638.67   567.9 2640.66
#Mann= 5, -1 ,  0
       0     0.1       0     140    0.06       0     203   0.045       0
   218.4    0.06       0  371.85     0.1       0
#XS Ineff= 2 , 0
                          258.54          2589.2
Permanent Ineff=
       F       F
Bank Sta=203,218.4
XS Rating Curve= 0 ,0
Exp/Cntr(USF)=0,0
Exp/Cntr=0.3,0.1

Type RM Length L Ch R = 1 ,3539    ,40.6,40.9,40.9
XS GIS Cut Line= 6
2230421.52195994577705.0317352792230311.00165494577520.139946179
2230284.59459623577520.6493553382230247.71053885577522.570399993
2230235.03164413577523.7230267862229986.31001872577235.288891937
#Sta/Elev= 30
       0 2667.77    60.4 2655.81    83.7 2650.12   114.6 2636.08   130.3 2627.75
   153.6 2613.03   209.5 2584.75   218.2 2581.96   242.2 2579.89  249.222575.866
   254.3 2574.91   269.4 2575.85   282.3 2577.89   300.1 2578.82   357.1 2575.46
   384.6  2583.5   421.6  2585.3   471.2 2582.39   519.4 2585.71   532.5  2583.7
   542.1 2583.56   548.4 2585.53   553.7 2588.89   576.1 2609.12   583.7 2613.94
   611.8 2625.92   622.3 2631.97   638.5 2633.98   657.2  2644.8   672.3  2649.5
#Mann= 4, -1 ,  0
       0     0.1       0     120    0.06       0  249.22   0.045       0
   269.4     0.1       0
#XS Ineff= 2 , 0
                          296.65         2583.63
Permanent Ineff=
       F       F
Bank Sta=249.22,269.4
XS Rating Curve= 0 ,0
Exp/Cntr(USF)=0,0
Exp/Cntr=0.3,0.1

Type RM Length L Ch R = 1 ,3498    ,260.8,271.2,278.9
XS GIS Cut Line= 6
2230420.56802555577664.8979765712230310.04772056 577480.00618747
2230283.64066185577480.5155966292230246.75660447577482.436641284
2230234.07770975577483.5892680772229985.35608434577195.155133228
#Sta/Elev= 30
       0 2662.58    32.3 2655.19    49.7 2648.91    78.8 2635.02   144.1 2598.03
   181.4 2581.79   200.1 2579.77   215.4 2576.03   237.3 2577.19  246.272574.362
   253.4 2573.56   264.8 2574.39   289.4 2577.51   343.4 2573.67   356.9 2575.97
     374 2583.45   382.5 2584.48   416.5 2583.96   435.3 2581.56   479.5 2584.82
   501.6 2582.34   510.1 2583.23   515.8    2585   532.8 2595.74   542.9 2607.13
   557.8 2616.99   595.7 2634.08   612.2 2636.29   631.3 2646.84   672.3 2659.78
#Mann= 4, -1 ,  0
       0     0.1       0     120    0.06       0  246.27   0.045       0
   264.8     0.1       0
#XS Ineff= 2 , 0
          235.94 2585.01  288.85          2584.4
Permanent Ineff=
       F       F
Bank Sta=246.27,264.8
XS Rating Curve= 0 ,0
Exp/Cntr(USF)=0,0
Exp/Cntr=0.3,0.1

Type RM Length L Ch R = 1 ,3227    ,301.1,298.2,294
XS GIS Cut Line= 4
2230551.12347518577593.5448376882230471.24926507577422.299239052
2230356.96562847577221.0742002942230217.25858084577090.324004665
#Sta/Elev= 30
       0 2667.32    20.6 2658.86      49 2645.48   115.2 2604.85   141.6 2591.14
   168.1 2580.27   186.1 2575.88   195.2 2572.14   217.8 2571.61   230.2 2568.71
   265.4 2568.17  290.162563.345     296  2562.4  311.642563.343   323.6 2568.82
   328.2 2569.86   346.6 2568.49   365.1 2571.71   369.6 2571.92   378.8 2570.26
   388.6 2573.11   420.3 2571.22     469 2575.09   496.3 2582.88   513.9 2585.23
   528.4 2591.97   543.1 2601.85     568 2616.45     590 2627.21   611.7 2639.99
#Mann= 5, -1 ,  0
       0     0.1       0     140    0.06       0  248.96     0.1       0
  290.16   0.045       0  311.64     0.1       0
Bank Sta=290.16,311.64
XS Rating Curve= 0 ,0
Exp/Cntr=0.3,0.1

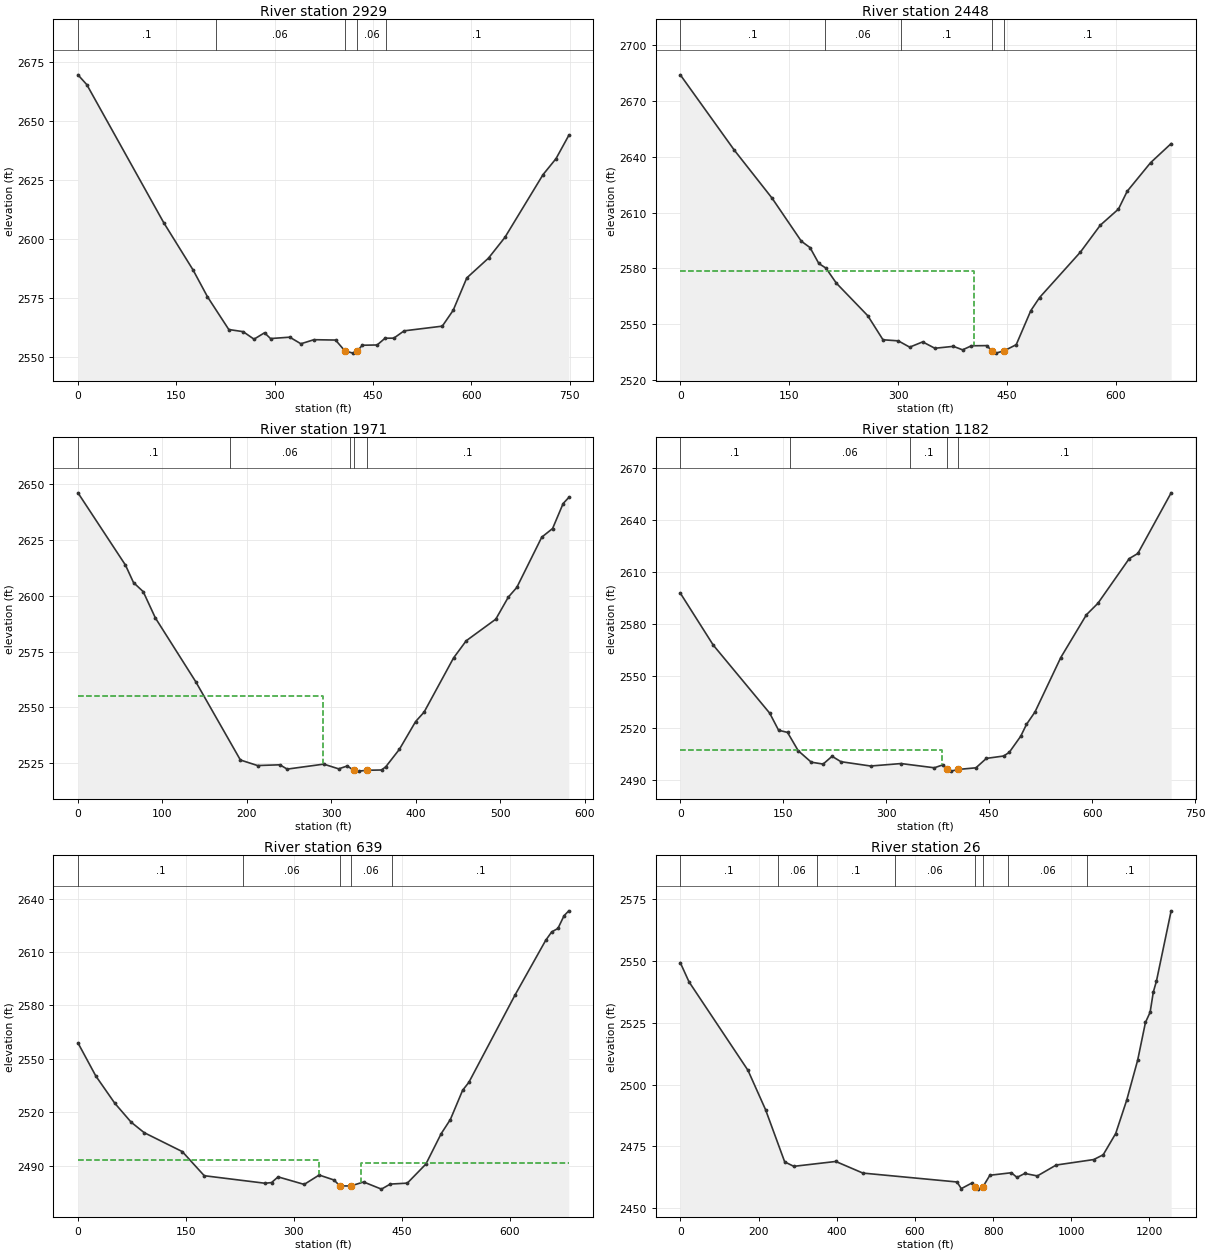
Type RM Length L Ch R = 1 ,2929    ,469.6,481,488.2
XS GIS Cut Line= 4
2230778.66033377577474.1256779562230690.96839414577187.868578873
2230544.36247451 577060.998236542230298.33454647576991.896523178
#Sta/Elev= 30
       0 2669.55    13.5 2665.38   130.8 2606.83   175.7 2586.69   197.6 2575.35
   230.1 2561.46     252 2560.55   268.6 2557.36   284.6 2560.07   293.8 2557.62
   323.1 2558.21   340.1 2555.41     360 2557.14     393 2556.99  407.172552.406
   419.5 2551.44  426.372552.406   433.7 2554.79   456.4  2554.9   468.5 2557.77
   481.9  2557.8   497.6  2560.9   555.8 2562.89   572.4 2569.61   593.2 2583.37
   626.3 2591.76   651.3 2600.55   709.5  2627.2   729.3 2633.98   748.8 2643.87
#Mann= 5, -1 ,  0
       0     0.1       0     210    0.06       0  407.17   0.045       0
  426.37    0.06       0  469.39     0.1       0
Bank Sta=407.17,426.37
XS Rating Curve= 0 ,0
Exp/Cntr=0.3,0.1

Type RM Length L Ch R = 1 ,2448    ,474.1,477.1,482.1
XS GIS Cut Line= 5
2230962.30732327577475.1094209642230990.72668576577192.683487834
2231033.12691063577068.261153132     2231041.701577008.400872117
2231063.59665722576808.961590175
#Sta/Elev= 30
       0 2683.95    74.3 2643.56   126.6 2617.65   166.8  2594.6   178.8 2591.17
   190.9 2582.64   200.7 2580.16     215  2572.1   258.4 2554.57   279.3 2541.68
   300.4  2541.1   316.1 2537.72     334 2540.55   350.8 2537.12   376.3 2538.15
     389 2536.28   401.2 2538.45   422.5 2538.55  429.242535.663   434.6 2534.51
  445.772535.661   462.9 2539.04     483 2557.32   495.1 2564.37   551.4 2588.78
   578.8 2603.22   603.8 2611.86   615.8 2621.41     648 2636.75   676.4 2647.03
#Mann= 5, -1 ,  0
       0     0.1       0     200    0.06       0  303.85     0.1       0
  429.24   0.045       0  445.77     0.1       0
#XS Ineff= 2 , 0
          404.28 2578.53
Permanent Ineff=
       F       F
Bank Sta=429.24,445.77
XS Rating Curve= 0 ,0
Exp/Cntr=0.3,0.1

Type RM Length L Ch R = 1 ,1971    ,791.2,788.9,780.1
XS GIS Cut Line= 4
2231252.84935105577533.0928988632231365.14759601 577365.33175687
2231478.28413871577220.9584632932231595.61889226577063.875348695
#Sta/Elev= 30
       0 2645.99    56.3 2613.64    65.8 2605.84    77.3 2601.78    91.7 2590.02
   139.5  2561.5   192.4 2526.47   212.7 2523.99   239.2 2524.32   247.8 2522.39
   291.1 2524.62   308.8 2522.51     319 2523.79   326.7 2521.87   332.4 2521.49
   342.62521.873   359.6    2522   364.7 2523.48   380.8 2531.29     400 2543.69
     410 2547.89   444.9 2572.13   459.9 2579.81   494.9 2589.46   509.8 2599.35
   519.8 2603.66   549.4 2626.17   562.2 2630.02   574.7 2641.21   581.4 2643.92
#Mann= 5, -1 ,  0
       0     0.1       0     180    0.06       0  321.88     0.1       0
   326.7   0.045       0   342.6     0.1       0
#XS Ineff= 2 , 0
          289.77  2555.1
Permanent Ineff=
       F       F
Bank Sta=326.7,342.6
XS Rating Curve= 0 ,0
Exp/Cntr=0.3,0.1

Type RM Length L Ch R = 1 ,1182    ,544.5,542.4,538.9
XS GIS Cut Line= 4
 2231780.2762392577981.5897010542231884.98698211577727.344230604
2231913.03044147577530.6376026172231979.77418754577298.559069254
#Sta/Elev= 30
       0 2597.68      48 2567.68   130.2 2528.44   143.2 2518.57   156.2 2517.32
   171.8 2506.74   190.8 2500.13   208.1 2499.05   221.1 2503.54     234 2500.43
   277.2 2497.93   321.6 2499.35   370.1 2496.91   382.2 2498.56   388.72495.962
   394.3 2494.98  405.232495.962   430.7  2496.9   445.9 2502.33   471.1  2503.7
   479.3 2505.84     496 2515.14   504.3 2521.92   516.8 2529.15   554.3  2560.5
   591.7 2585.21   608.4 2591.79   654.1  2617.6   666.6 2620.55   715.1 2655.52
#Mann= 5, -1 ,  0
       0     0.1       0     160    0.06       0  334.96     0.1       0
   388.7   0.045       0  405.23     0.1       0
#XS Ineff= 2 , 0
          381.65 2507.16
Permanent Ineff=
       F       F
Bank Sta=388.7,405.23
XS Rating Curve= 0 ,0
Exp/Cntr(USF)=0,0
Exp/Cntr=0.3,0.1

Type RM Length L Ch R = 1 ,639     ,620.1,613.6,606.4
XS GIS Cut Line= 4
 2232251.6726018  578062.30567432232400.98651099577783.688385992
2232360.32115371577618.5610731682232291.69806949 577435.03818209
#Sta/Elev= 30
       0  2558.9    24.8 2540.32    51.2    2525    73.9 2514.37      92 2508.49
     145 2497.84   175.5  2484.3     260 2480.06     269 2480.44   278.1 2483.64
   314.4 2479.41   335.2 2484.68   355.8 2481.89     364 2478.55  379.162478.549
     397 2480.78   421.7 2476.76     434 2479.59   457.7 2480.13   483.5 2490.83
   504.7 2507.88   517.5 2515.86   534.6 2532.33   543.2 2536.73   607.2 2585.67
   649.9 2616.46   658.3 2621.24     667  2623.2   675.5 2630.34   682.1 2633.09
#Mann= 5, -1 ,  0
       0     0.1       0     230    0.06       0     364   0.045       0
  379.16    0.06       0   436.1     0.1       0
#XS Ineff= 2 ,-1
       0  335.15 2493.37  393.42682.0988 2491.17
Permanent Ineff=
       F       F
Bank Sta=364,379.16
XS Rating Curve= 0 ,0
Exp/Cntr(USF)=0,0
Exp/Cntr=0.3,0.1

Type RM Length L Ch R = 1 ,26      ,,,
XS GIS Cut Line= 4
2232771.46879183578202.8206531872232916.47556694577489.958141538
2232809.85118816577426.8460808292232406.62099469577452.116376937
#Sta/Elev= 30
       0 2549.28    22.3 2541.53   173.1 2505.74     218 2489.84     267 2468.71
   290.3 2466.91   397.6 2468.88     467 2464.18   707.8 2460.58   718.6 2457.89
   745.8 2460.17  753.43 2458.51   760.3 2457.69   773.42458.483   791.8  2463.3
   846.8 2464.32   861.1 2462.43   881.1 2464.03   913.2 2463.03   961.3 2467.43
  1057.4 2469.65  1081.6 2471.58  1113.6 2480.19  1141.8 2493.71  1169.7 2509.81
  1189.7 2525.12  1201.7 2529.26  1209.7 2537.36  1217.8 2541.83  1255.4 2570.26
#Mann= 8, -1 ,  0
       0     0.1       0     250    0.06       0     350     0.1       0
     550    0.06       0  753.43   0.045       0   773.4     0.1       0
  837.46    0.06       0 1041.36     0.1       0
Bank Sta=753.43,773.4
XS Rating Curve= 0 ,0
Exp/Cntr(USF)=0,0
Exp/Cntr=0.3,0.1
LCMann Table=0

Chan Stop Cuts=-1
Use User Specified Reach Order=0
Composite Channel Slope=5